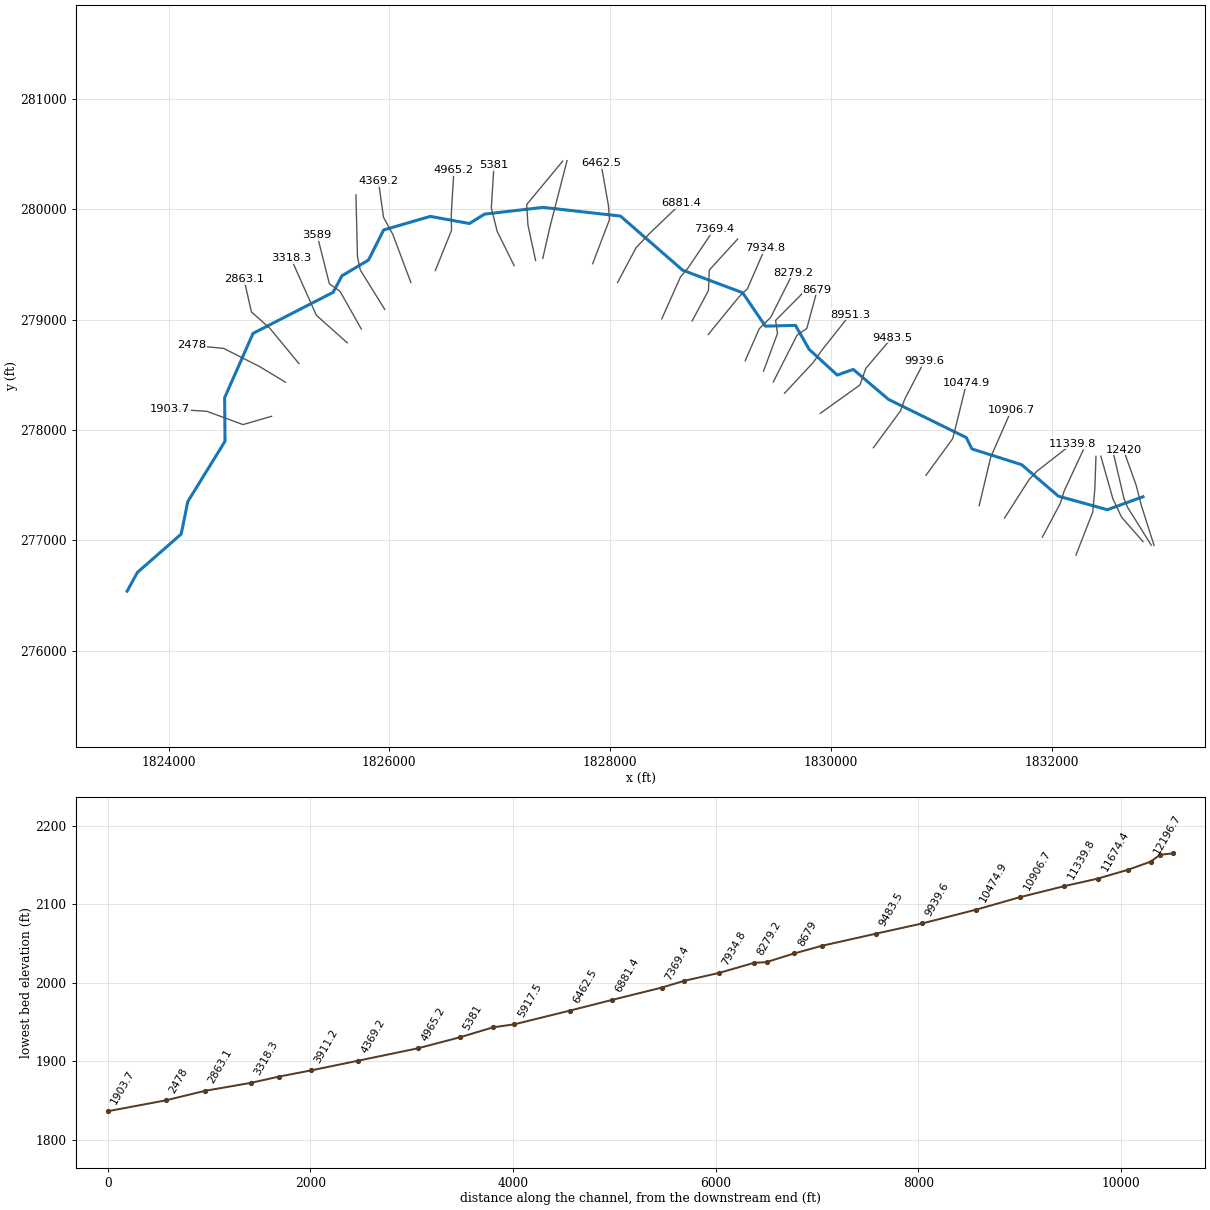
--- ClearFk.prj (project) ---

Proj Title=ClearFk
Current Plan=p01
Default Exp/Contr=0,0
English Units
Geom File=g01
Flow File=f01
Plan File=p01
BEGIN DESCRIPTION:
END DESCRIPTION:
DSS Export Rating Curves= 0
DSS Export Rating Curve Sorted= 0
DSS Export Volume Flow Curves= 0
DXF OffsetX= 0
DXF OffsetY= 0
DXF ScaleX= 0
DXF ScaleY= 0

--- ClearFk.p01 (plan) ---

Plan Title=Floodplain
Program Version=4.00
Geom File=g01
Flow File=f01
K Sum by GR=0
Std Step Tol=0.01
Critical Tol=0.01
Num of Std Step Trials=20
Max Error Tol=0.3
Flow Tol Ratio=0.001
Split Flow NTrial=30
Split Flow Tol=0.02
Split Flow Ratio=0.02
Log Output Level=0
Friction Slope Method=1
Unsteady Friction Slope Method=2
Unsteady Bridges Friction Slope Method=1
Global Log Level=0
CheckData=False
Run HTab=0
Run UNet=0
Run PostProcess=0
UNET Theta=0
UNET Theta Warmup=0
UNET ZTol=0
UNET ZSATol=0
UNET MxIter=0
UNET MaxInSteps=0
UNET DtIC=0
UNET DtMin=0
UNET MaxCRTS=0
UNET WFStab=0
UNET SFStab=0
UNET WFX=0
UNET SFX=0
UNET DSS MLevel=0
UNET DZMax Abort=0
UNET Convert EG Bridges=0
UNET Use Existing IB Tables=0
UNET Froude Limit=0
UNET Froude Power=0
Write IC File=0
Echo Input=False
Echo Output=False
Write Detailed=0

--- ClearFk.f01 (steady flow) ---

Flow Title=NFF Regression Equation
Program Version=4.00
Number of Profiles=1
Profile Names=P100yr
River Rch & RM=ClearFk,Main      ,12420
547.4411
River Rch & RM=ClearFk,Main      ,12288.9
548.6046
River Rch & RM=ClearFk,Main      ,11971.1
689.7134
River Rch & RM=ClearFk,Main      ,11674.4
746.9942
River Rch & RM=ClearFk,Main      ,10474.9
799.8720
River Rch & RM=ClearFk,Main      ,8679
861.4811
River Rch & RM=ClearFk,Main      ,5706.2
942.2778
River Rch & RM=ClearFk,Main      ,5381
1405.324
River Rch & RM=ClearFk,Main      ,3589
1522.932
River Rch & RM=ClearFk,Main      ,276.8
1656.168
Boundary for River Rch & Prof#=ClearFk,Main      ,1
Up Type=0
Dn Type=3
Dn Slope=0.023517

--- ClearFk.g01 (geometry) ---

Geom Title=USGS 10m DEM
Program Version=4.00

River Reach=ClearFk         ,Main
Reach XY= 30
     1832826.689       277395.56     1832503.685      277278.183
     1832059.433      277401.446     1831727.415      277686.229
     1831277.081      277828.851     1831226.178      277931.574
     1830521.327       278277.35     1830202.608      278548.834
     1830056.777      278497.931     1829803.178      278730.435
       1829678.9      278947.806      1829406.04      278940.927
     1829200.592      279243.137     1828656.269      279447.972
      1828093.56      279937.899     1827392.031      280016.638
     1826861.919      279955.594     1826725.678      279870.381
     1826370.952      279935.027     1825948.266      279811.951
     1825811.333      279539.536     1825570.749      279396.723
      1825490.77      279247.125     1824765.515      278875.288
     1824508.541      278292.969     1824511.754      277897.795
      1824174.41      277351.618     1824114.973      277057.647
     1823718.154      276710.001     1823625.278      276540.963

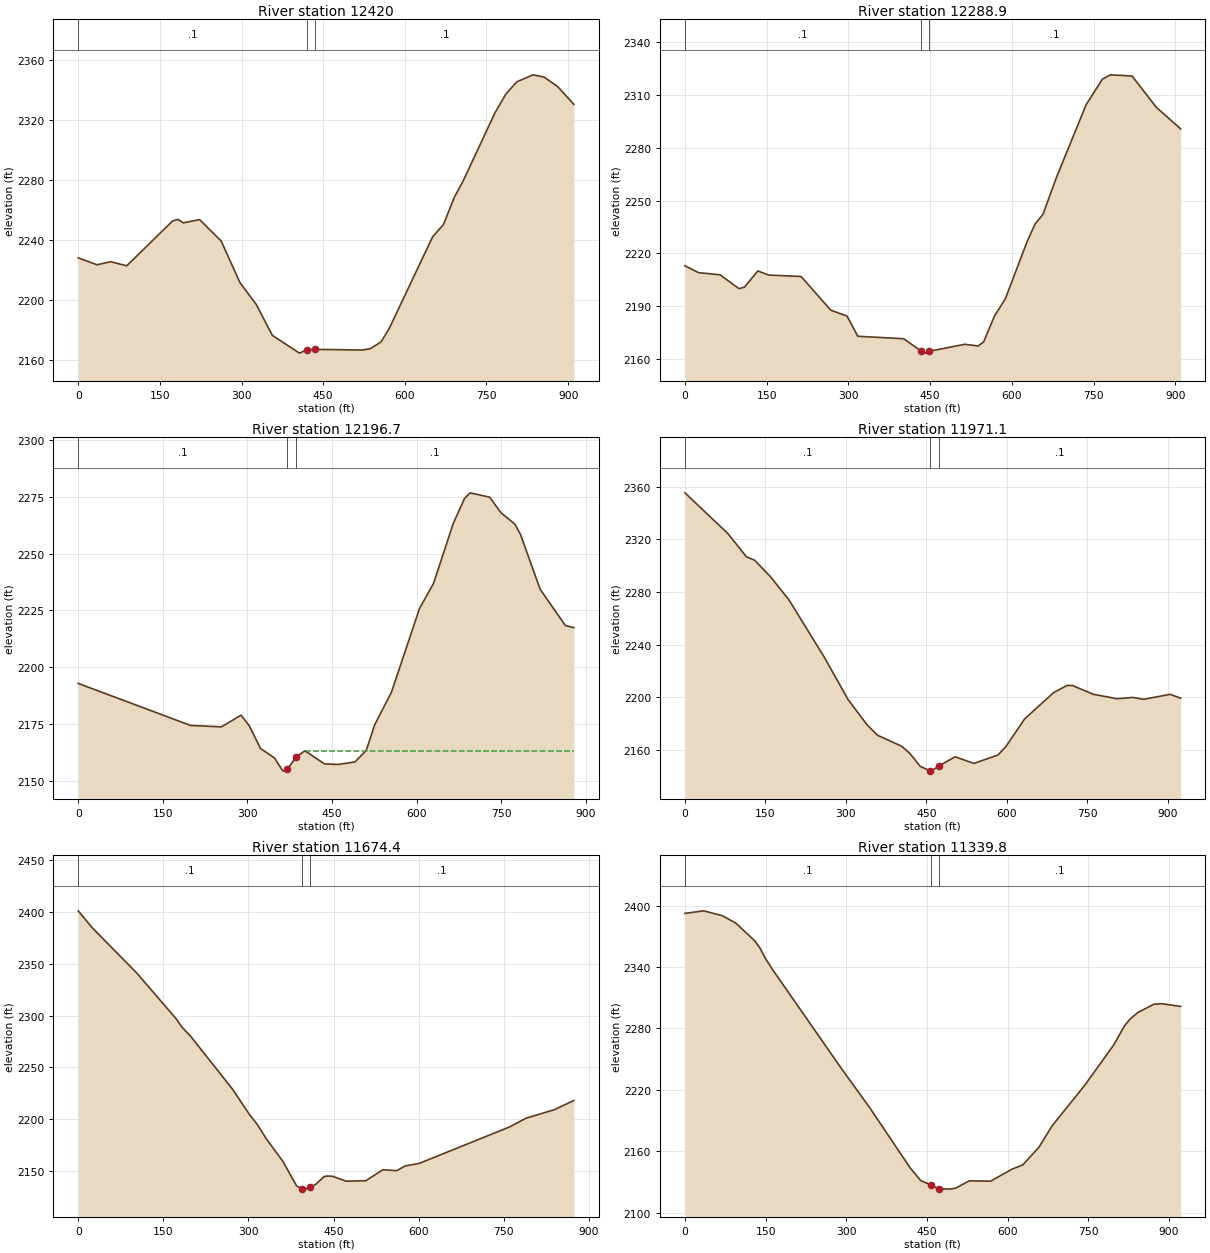
Type RM Length L Ch R = 1 ,12420   ,128.2,131.1,135.6
XS GIS Cut Line= 4
      1832926.79      276954.687     1832812.611      277313.437
     1832763.782      277501.918      1832649.58      277821.436
#Sta/Elev= 30
       0 2228.21    34.7 2223.61    59.4 2225.66    89.2 2222.92   173.4 2252.82
   183.3 2253.83   193.2 2251.53   222.9 2253.74   262.6 2239.46   297.2 2211.68
     327 2197.18   356.7 2176.56   406.4 2164.73   419.9  2166.9   434.9 2167.24
   521.3 2166.81   536.2 2167.66   556.2 2172.16   571.2 2181.08     651 2242.19
     671 2250.46   690.9 2268.59   705.9 2278.56   765.8 2325.03   785.8 2337.47
   805.7 2345.56   835.6 2350.19   855.6  2348.7   880.6 2342.42   910.5 2330.51
#Mann= 3 , 0 , 0
       0      .1       0   419.9    .045       0   434.9      .1       0
Bank Sta=419.9,434.9
XS Rating Curve= 0 ,0
Exp/Cntr=0.3,0.1

Type RM Length L Ch R = 1 ,12288.9 ,90.8,92.3,93.7
XS GIS Cut Line= 4
      1832901.18      276956.917     1832685.898      277301.832
     1832653.489      277382.852      1832558.58      277787.954
#Sta/Elev= 30
       0 2212.89    24.8 2208.97    64.5 2207.73    99.2 2199.86   109.1 2200.71
   133.9 2209.94   153.7 2207.59   213.2 2206.77   267.8 2187.55   297.5 2184.25
   317.3 2172.75   401.6 2171.33     433 2164.46   440.5 2163.14     448 2164.18
   513.7 2168.18   538.4  2167.2   548.3 2169.59   568.2 2184.29     588 2193.98
   627.6 2226.26   642.4 2236.49   657.3 2242.26   682.1  2263.3   736.6  2304.7
   766.3 2319.14   781.1 2321.59   820.8  2320.9   865.3  2303.1   909.9 2290.82
#Mann= 3 , 0 , 0
       0      .1       0     433    .045       0     448      .1       0
Bank Sta=433,448
XS Rating Curve= 0 ,0
Exp/Cntr=0.3,0.1

Type RM Length L Ch R = 1 ,12196.7 ,238.1,225.6,213.1
XS GIS Cut Line= 4
     1832826.236      276990.053      1832632.44      277210.663
     1832554.435      277375.207     1832444.739      277762.798
#Sta/Elev= 30
       0  2192.9   199.1 2174.42   253.8 2173.78   288.7 2178.94   303.5 2174.16
   323.2 2164.26   347.8 2160.15   362.5 2154.48   367.5 2154.32   370.8 2155.18
   385.8  2160.4   401.9 2163.29   436.4 2157.51     461 2157.25   490.7 2158.38
   510.6 2163.43   525.5 2174.68   555.3 2189.06     605 2225.84   629.9 2236.92
   664.7 2263.15   684.6 2274.18   694.6 2276.71   729.4 2274.79   749.3 2267.98
   774.1 2262.94   784.1 2258.34   818.9 2234.26   863.6 2218.34   878.6 2217.43
#Mann= 3 , 0 , 0
       0      .1       0   370.8    .045       0   385.8      .1       0
#XS Ineff= 2 , 0
                          402.13         2163.27
Permanent Ineff=
       F       F
Bank Sta=370.8,385.8
XS Rating Curve= 0 ,0
Exp/Cntr=0.3,0.1

Type RM Length L Ch R = 1 ,11971.1 ,301.4,296.6,291.8
XS GIS Cut Line= 4
     1832219.457       276867.13     1832371.466      277257.465
     1832389.985      277461.173     1832400.564      277761.614
#Sta/Elev= 30
       0 2355.38    79.8  2324.5   114.7 2306.71   129.7 2304.21   159.6 2291.56
   194.5 2273.66   259.3 2230.74   304.2  2198.2   339.1 2179.28     359 2171.12
   403.9 2162.81   418.9 2157.47   438.8 2147.44   457.7 2143.96   458.8 2143.85
   472.7 2147.59   503.7 2154.77   538.6  2149.7   583.5 2156.08   598.5 2162.64
   633.3 2183.54   687.5 2203.59   712.2 2208.95     722 2208.99   761.4 2202.25
   805.8 2198.88   835.4 2199.86   855.1 2198.42   904.4 2202.23   924.1 2199.31
#Mann= 3 , 0 , 0
       0      .1       0   457.7    .045       0   472.7      .1       0
Bank Sta=457.7,472.7
XS Rating Curve= 0 ,0
Exp/Cntr=0.3,0.1

Type RM Length L Ch R = 1 ,11674.4 ,344.9,334.7,324.5
XS GIS Cut Line= 4
     1831915.437      277030.608     1832077.478       277336.17
     1832112.201      277447.284     1832285.816      277819.977
#Sta/Elev= 30
       0 2401.08    24.7 2384.77   103.8 2340.73   172.9 2296.78   182.8  2288.9
   197.6 2280.46   271.8 2229.19   301.4 2204.95   316.2 2194.61     331 2181.59
   360.4 2159.69   384.7 2135.96   393.9 2132.92   399.2 2132.69   408.9 2134.56
   408.9 2134.57   418.6 2137.35   433.2 2144.75     438 2145.33   447.7 2145.15
   472.2 2140.35   506.9  2140.8   536.6 2151.35   561.4 2150.49   576.2 2155.07
     601 2157.52   759.5 2192.54   789.2  2201.1   838.8 2209.24   873.4 2218.18
#Mann= 3 , 0 , 0
       0      .1       0   393.9    .045       0   408.9      .1       0
Bank Sta=393.9,408.9
XS Rating Curve= 0 ,0
Exp/Cntr=0.3,0.1

Type RM Length L Ch R = 1 ,11339.8 ,421.3,433.1,441.7
XS GIS Cut Line= 4
     1831571.997       277202.82     1831795.064      277551.453
     1831866.825      277627.843     1832184.628      277875.712
#Sta/Elev= 30
       0 2392.55    34.9 2395.04    69.8 2390.24    94.8 2382.94   129.6 2365.78
   139.6 2358.57   149.6 2348.52   164.6  2336.3   289.2 2242.19   344.1 2202.13
   418.9 2143.62   438.8  2131.1   456.8 2127.15   471.8 2123.28   493.7 2122.93
   503.7 2123.98   528.6 2131.03   568.5 2130.76   608.3 2142.49   628.2 2146.62
     658 2163.75   682.9 2184.94   742.6 2223.95   797.3  2263.9   817.2 2282.55
   827.2 2288.97   842.1 2295.64     872 2303.73   886.9 2304.21   921.7 2301.61
#Mann= 3 , 0 , 0
       0      .1       0   456.8    .045       0   471.8      .1       0
Bank Sta=456.8,471.8
XS Rating Curve= 0 ,0
Exp/Cntr=0.3,0.1

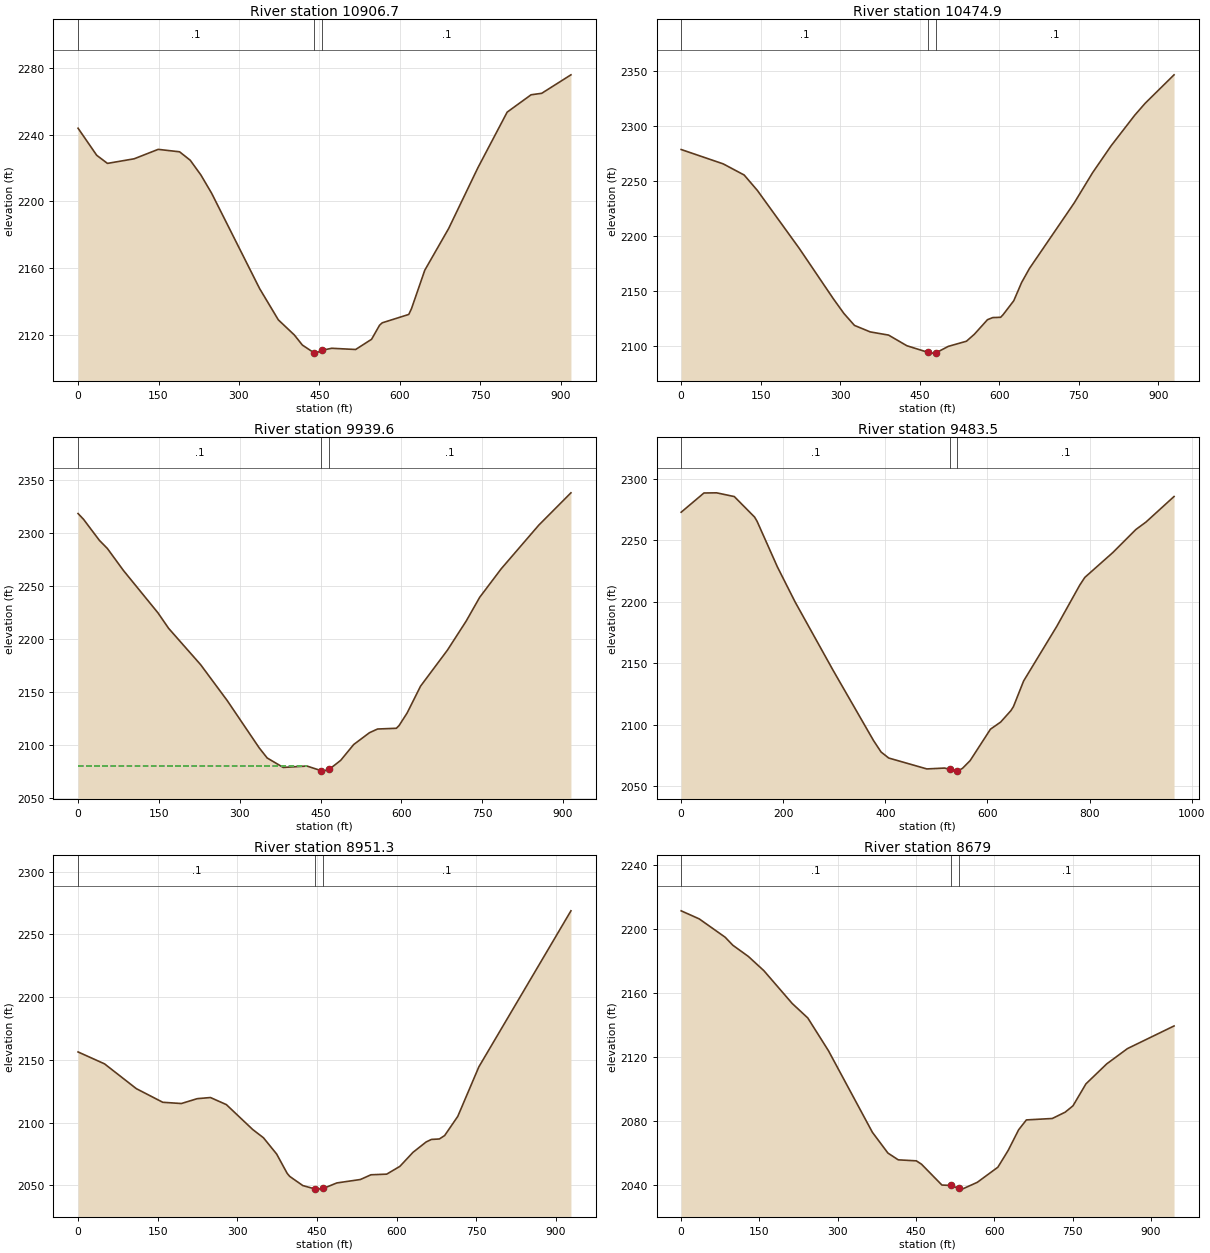
Type RM Length L Ch R = 1 ,10906.7 ,432.1,431.8,434.7
XS GIS Cut Line= 3
     1831342.433       277313.86      1831447.38       277754.63
      1831634.76      278181.094
#Sta/Elev= 30
       0 2243.94    34.8  2227.7    54.8 2222.84   104.6  2225.6   149.4 2231.26
   189.2  2229.8   209.1 2224.75     229 2215.89     249 2204.95   338.6 2147.66
   373.4 2128.96   403.3 2119.87   418.2 2113.84   440.4 2109.09   443.1    2109
   455.4 2110.75   472.9 2111.91   517.5 2111.18   547.2 2117.31   562.1 2125.73
   567.1 2127.19   616.6 2132.22   621.6 2135.66   646.4 2158.74     691 2183.82
   745.5 2220.27     800  2253.6   844.6 2264.01   864.4 2264.89   918.9 2275.98
#Mann= 3 , 0 , 0
       0      .1       0   440.4    .045       0   455.4      .1       0
Bank Sta=440.4,455.4
XS Rating Curve= 0 ,0
Exp/Cntr=0.3,0.1

Type RM Length L Ch R = 1 ,10474.9 ,536.9,535.3,533.7
XS GIS Cut Line= 4
     1830860.485      277589.737     1831102.919      277921.832
     1831130.697       278030.63     1831227.857      278425.379
#Sta/Elev= 30
       0  2278.4    79.3 2265.34   118.9 2255.19   143.7 2241.23   222.9  2188.4
   287.3  2142.5   307.1 2129.23     327 2118.36   356.7 2112.46   391.4 2109.54
   425.8 2099.88   466.5 2093.72   474.6 2093.14   481.5 2093.56   503.9 2099.26
   538.3 2103.97   553.2  2110.3     578 2123.57   587.9 2125.48   602.8 2125.74
   607.7 2128.26   627.6 2140.82   642.4 2157.42   657.3 2170.26   741.6 2229.78
   776.3 2257.28     811 2281.61   855.6 2309.46   875.4 2320.41     930 2346.35
#Mann= 3 , 0 , 0
       0      .1       0   466.5    .045       0   481.5      .1       0
Bank Sta=466.5,481.5
XS Rating Curve= 0 ,0
Exp/Cntr=0.3,0.1

Type RM Length L Ch R = 1 ,9939.6  ,455.9,456.1,456.2
XS GIS Cut Line= 4
     1830384.594      277839.594     1830630.686      278174.152
     1830667.723      278278.321     1830846.555      278623.623
#Sta/Elev= 30
       0 2318.41     9.9 2313.14    39.6 2293.11    54.4 2285.46      84 2264.84
   148.3 2224.73   168.1 2210.12   227.4 2175.91   276.9 2141.95   336.2 2097.38
     351 2087.85   380.7 2078.95   424.9 2080.24   450.8 2075.95   453.8 2075.46
   465.8 2077.07   487.4 2085.61   511.5 2100.54   540.8  2111.7   555.8 2115.18
   590.7 2115.87   595.7 2118.41   610.6 2130.21   635.6  2155.6   685.4 2189.51
   720.3 2216.99   745.2 2239.28   785.1 2266.18   854.9  2307.4   914.7 2337.95
#Mann= 3 , 0 , 0
       0      .1       0   450.8    .045       0   465.8      .1       0
#XS Ineff= 2 , 0
          425.02 2080.23
Permanent Ineff=
       F       F
Bank Sta=450.8,465.8
XS Rating Curve= 0 ,0
Exp/Cntr=0.3,0.1

Type RM Length L Ch R = 1 ,9483.5  ,540.1,532.2,523.2
XS GIS Cut Line= 4
     1829903.817      278151.004     1830262.622      278407.954
     1830315.864       278558.42      1830551.98      278836.204
#Sta/Elev= 30
       0 2272.94    44.6 2288.58    69.4 2288.72   104.1 2285.68   143.8 2269.02
   148.8 2265.51   188.4  2228.6   223.1 2200.07   297.5  2144.5   376.9 2087.24
   391.7 2077.95   406.6 2073.09   481.2 2064.23   516.1 2064.93     526 2063.93
     541 2062.44     551 2064.68     566 2070.95   605.9 2096.54   625.9 2102.35
   645.9 2111.62   650.9 2114.88   670.8 2135.71   735.8 2180.17   780.7 2213.62
   790.7 2219.94   845.6 2240.17   890.6 2258.85   910.6 2264.98   965.5 2285.73
#Mann= 3 , 0 , 0
       0      .1       0     526    .045       0     541      .1       0
Bank Sta=526,541
XS Rating Curve= 0 ,0
Exp/Cntr=0.3,0.1

Type RM Length L Ch R = 1 ,8951.3  ,280.6,272.4,264.1
XS GIS Cut Line= 4
     1829579.523      278332.875     1829841.316      278613.977
     1829917.706      278722.776     1830173.228      279045.434
#Sta/Elev= 30
       0 2156.38    49.9 2146.88   109.8 2127.12   159.6 2116.26   194.6 2115.27
   224.5 2119.14   249.4 2120.05   279.4 2114.41   329.2  2094.5   349.2 2088.02
   374.2 2074.98     394 2059.59   398.9 2057.14   423.5 2049.86   446.9 2047.12
   448.1 2047.04   461.9 2047.57   487.5 2051.97   531.9 2054.71   551.8 2058.47
   581.5 2058.98   606.3 2065.18   631.1  2076.4   655.9 2084.67   665.8 2086.65
   680.7 2087.02   690.6 2089.72   715.4 2105.03   755.1 2144.48   928.6 2268.86
#Mann= 3 , 0 , 0
       0      .1       0   446.9    .045       0   461.9      .1       0
Bank Sta=446.9,461.9
XS Rating Curve= 0 ,0
Exp/Cntr=0.3,0.1

Type RM Length L Ch R = 1 ,8679    ,246.6,272.6,298.5
XS GIS Cut Line= 4
     1829477.882      278435.732     1829693.164      278859.353
     1829781.129       278919.54     1829876.039      279269.085
#Sta/Elev= 30
       0 2211.48    34.6 2206.44    84.2 2194.98      99 2189.94   128.7 2182.94
   158.4 2174.04   212.8 2153.46   242.5 2144.46   282.1 2123.95   366.3 2072.89
     396 2059.91   415.8 2055.67   450.4 2055.04   460.3 2052.94   499.4  2039.9
   516.7 2039.65   531.7  2037.8   538.2 2037.34   567.2  2041.6   606.6 2051.06
   626.4 2061.61   646.3 2074.44   661.2 2080.65   710.8 2081.54   735.6 2085.51
   750.5  2089.5   775.3 2103.22     815 2115.69   854.7 2125.26     944 2139.44
#Mann= 3 , 0 , 0
       0      .1       0   516.7    .045       0   531.7      .1       0
Bank Sta=516.7,531.7
XS Rating Curve= 0 ,0
Exp/Cntr=0.3,0.1

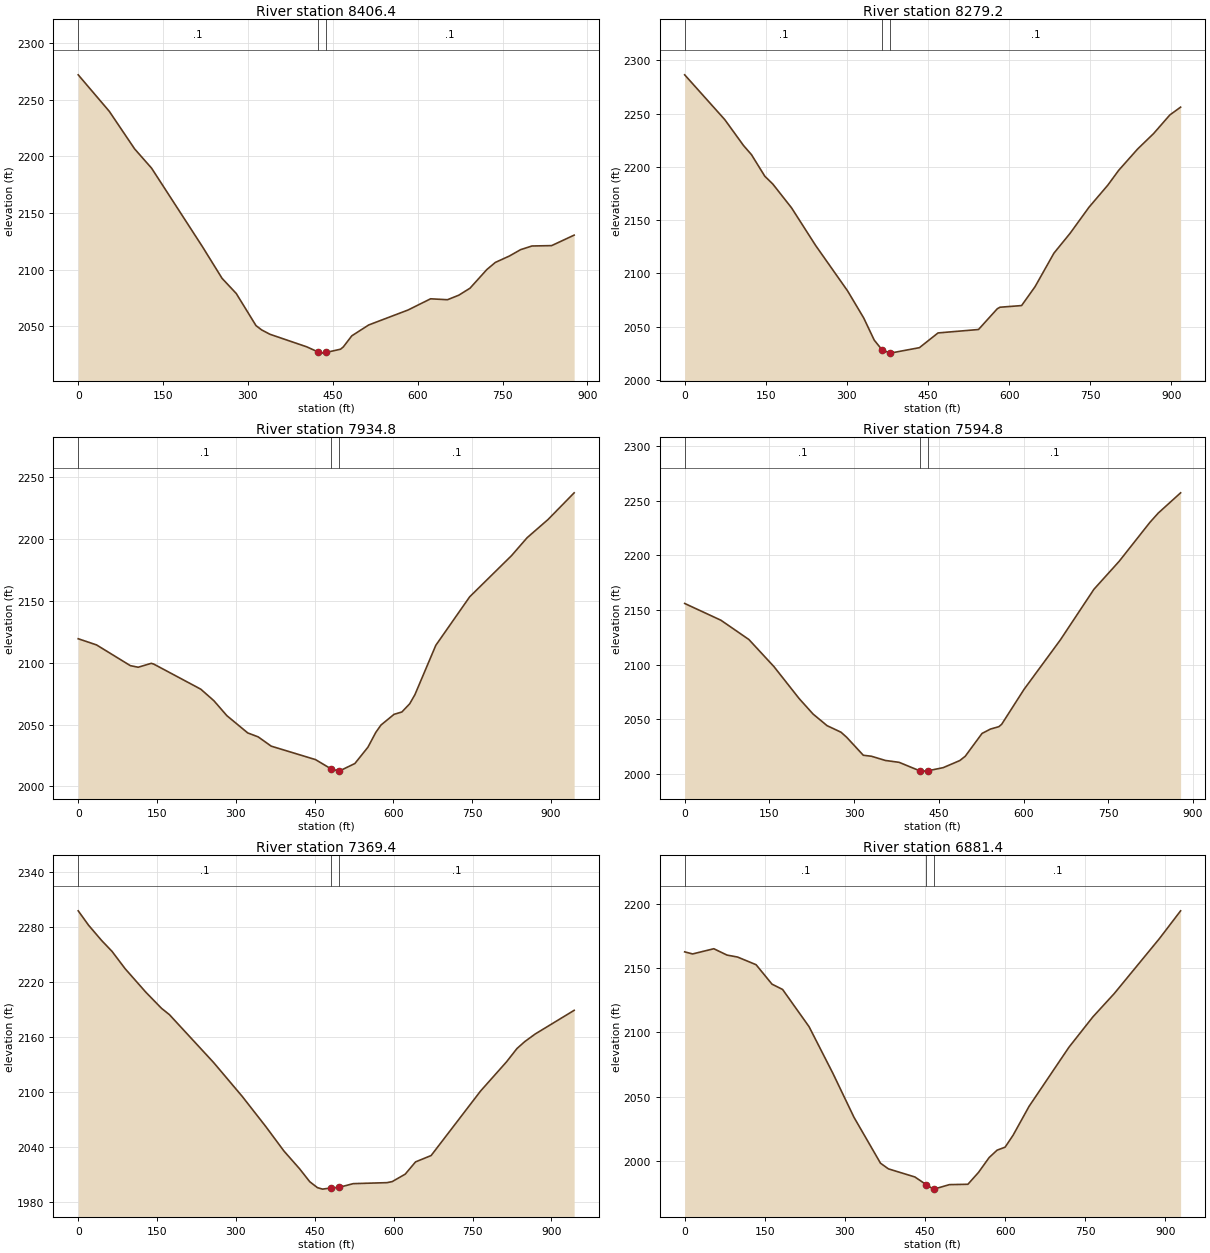
Type RM Length L Ch R = 1 ,8406.4  ,148.7,127.2,105.7
XS GIS Cut Line= 4
     1829389.108      278533.104     1829515.867      278874.379
     1829498.804      278992.607      1829775.48      279271.721
#Sta/Elev= 30
       0 2272.06    54.9 2239.85    99.7 2206.66   129.7 2189.61   219.4 2120.44
   254.3 2092.31   279.3 2078.99   314.2 2050.64   324.2 2046.82   339.1 2042.93
   403.9 2031.88     423 2027.56   433.7 2026.32     438  2026.9   463.6 2029.78
   468.6 2031.83   483.5 2041.59   513.4 2051.18     583 2064.41   622.8 2074.29
   652.6 2073.48   672.6 2077.47   692.4 2083.63   722.3 2100.17   737.2  2106.4
   762.1 2112.08     782 2117.71   801.9 2120.92   836.7 2121.25   876.5 2130.51
#Mann= 3 , 0 , 0
       0      .1       0     423    .045       0     438      .1       0
Bank Sta=423,438
XS Rating Curve= 0 ,0
Exp/Cntr=0.3,0.1

Type RM Length L Ch R = 1 ,8279.2  ,344.7,344.3,344
XS GIS Cut Line= 4
     1829223.246      278627.866     1829350.564      278917.225
     1829454.733      279021.394     1829658.441      279426.496
#Sta/Elev= 30
       0 2286.34    74.1 2244.34   108.7 2220.08   123.5 2211.43   148.2 2191.18
     163 2183.85   197.6 2161.52     242 2126.32   301.3 2083.52   330.9  2058.3
   350.5 2037.38   364.6 2028.53   379.6 2025.23     380 2025.22     434 2030.34
   468.4 2044.16   543.2 2047.38     578 2066.87     583 2068.29   622.9 2069.84
   647.8 2087.58   682.7 2119.02   712.6 2137.67   747.5  2162.1   782.4 2182.89
   802.3 2196.67   837.2 2216.62   867.1 2231.31     897  2248.7   916.9 2256.02
#Mann= 3 , 0 , 0
       0      .1       0   364.6    .045       0   379.6      .1       0
Bank Sta=364.6,379.6
XS Rating Curve= 0 ,0
Exp/Cntr=0.3,0.1

Type RM Length L Ch R = 1 ,7934.8  ,322.7,340,357.3
XS GIS Cut Line= 4
     1828889.031      278865.613     1829165.374      279204.268
      1829244.08      279280.659     1829402.503      279645.466
#Sta/Elev= 30
       0 2119.49    34.8 2114.53    99.3 2097.74   114.2 2096.45   139.1 2099.61
     144 2098.97   233.4 2078.71   258.3 2069.41   283.1 2057.29   322.9  2043.3
   342.7 2040.14   367.6 2032.62     452 2021.72   481.8 2014.19   496.8 2012.43
   496.9 2012.42   526.8 2018.54   551.8 2031.79   566.7 2043.72   576.6  2049.7
   601.5 2058.36   616.4 2060.26   631.3 2066.89   641.2 2074.22     681 2114.16
   745.6 2153.44   825.2  2186.7     855 2201.25   894.8 2215.95   944.5 2237.52
#Mann= 3 , 0 , 0
       0      .1       0   481.8    .045       0   496.8      .1       0
Bank Sta=481.8,496.8
XS Rating Curve= 0 ,0
Exp/Cntr=0.3,0.1

Type RM Length L Ch R = 1 ,7594.8  ,241.3,225.4,209.6
XS GIS Cut Line= 4
     1828743.123       278988.95     1828890.603      279263.189
     1828897.916      279448.453     1829155.091      279730.005
#Sta/Elev= 30
       0 2156.05    64.2 2140.67   113.7 2123.02   158.2 2098.14   202.6 2068.99
   227.4 2054.74   252.1 2044.15   276.8 2038.13   286.7 2033.57   316.3 2017.03
   330.9  2016.1   355.3 2012.28   379.7 2010.55   416.5 2002.72   423.6  2002.5
   431.5 2002.88   457.8  2005.7     487 2012.14   496.8 2016.14   526.5 2037.02
   541.4 2041.01   556.2  2043.2   561.2 2045.34   600.8 2077.33   665.2  2122.7
   724.6 2169.02   769.2 2194.59   823.6 2230.23   838.5 2238.82   878.1 2257.36
#Mann= 3 , 0 , 0
       0      .1       0   416.5    .045       0   431.5      .1       0
Bank Sta=416.5,431.5
XS Rating Curve= 0 ,0
Exp/Cntr=0.3,0.1

Type RM Length L Ch R = 1 ,7369.4  ,488.4,488,487.6
XS GIS Cut Line= 4
     1828467.775      279007.256     1828637.584      279387.143
     1828709.345      279472.793      1828941.26      279817.329
#Sta/Elev= 30
       0  2297.8    19.8 2282.01    44.6 2265.35    64.4 2253.45    89.2 2234.58
   128.8 2208.77   158.5 2191.24   173.4 2184.41   257.6    2132   312.1 2094.93
   356.7 2062.15   391.3 2035.34     421 2015.98   440.4 2001.81     455 1995.35
   464.7 1993.74   480.8 1995.06   495.8 1995.62     523 1999.73   587.2 2000.81
   597.1 2001.95   621.8 2010.04   641.6  2023.5   671.2 2030.44   765.2 2100.91
   814.6 2132.82   834.4 2147.32   849.2 2154.88     869 2163.18   943.2 2189.09
#Mann= 3 , 0 , 0
       0      .1       0   480.8    .045       0   495.8      .1       0
Bank Sta=480.8,495.8
XS Rating Curve= 0 ,0
Exp/Cntr=0.3,0.1

Type RM Length L Ch R = 1 ,6881.4  ,399.9,418.9,437.8
XS GIS Cut Line= 4
     1828067.289      279336.188     1828234.798      279651.038
     1828357.486       279780.67     1828641.689      280052.572
#Sta/Elev= 30
       0 2162.51    14.9 2160.89    54.5 2164.94    79.2 2160.02    99.1 2158.47
   133.7 2152.52   163.5 2137.41   183.3 2133.29   232.8  2104.4   277.4 2068.16
     317  2033.9   366.6 1998.27   381.4 1993.87     431 1987.56   451.9 1981.68
   465.7 1978.12   466.9 1978.14   495.5 1981.61   530.2 1981.89   550.1 1991.14
     570 2002.68   584.9  2008.4   599.8 2010.72   614.8    2020   644.6 2042.38
   719.3 2088.37   764.1 2111.95     804 2130.03   888.6 2172.76   928.4  2194.4
#Mann= 3 , 0 , 0
       0      .1       0   451.9    .045       0   466.9      .1       0
Bank Sta=451.9,466.9
XS Rating Curve= 0 ,0
Exp/Cntr=0.3,0.1

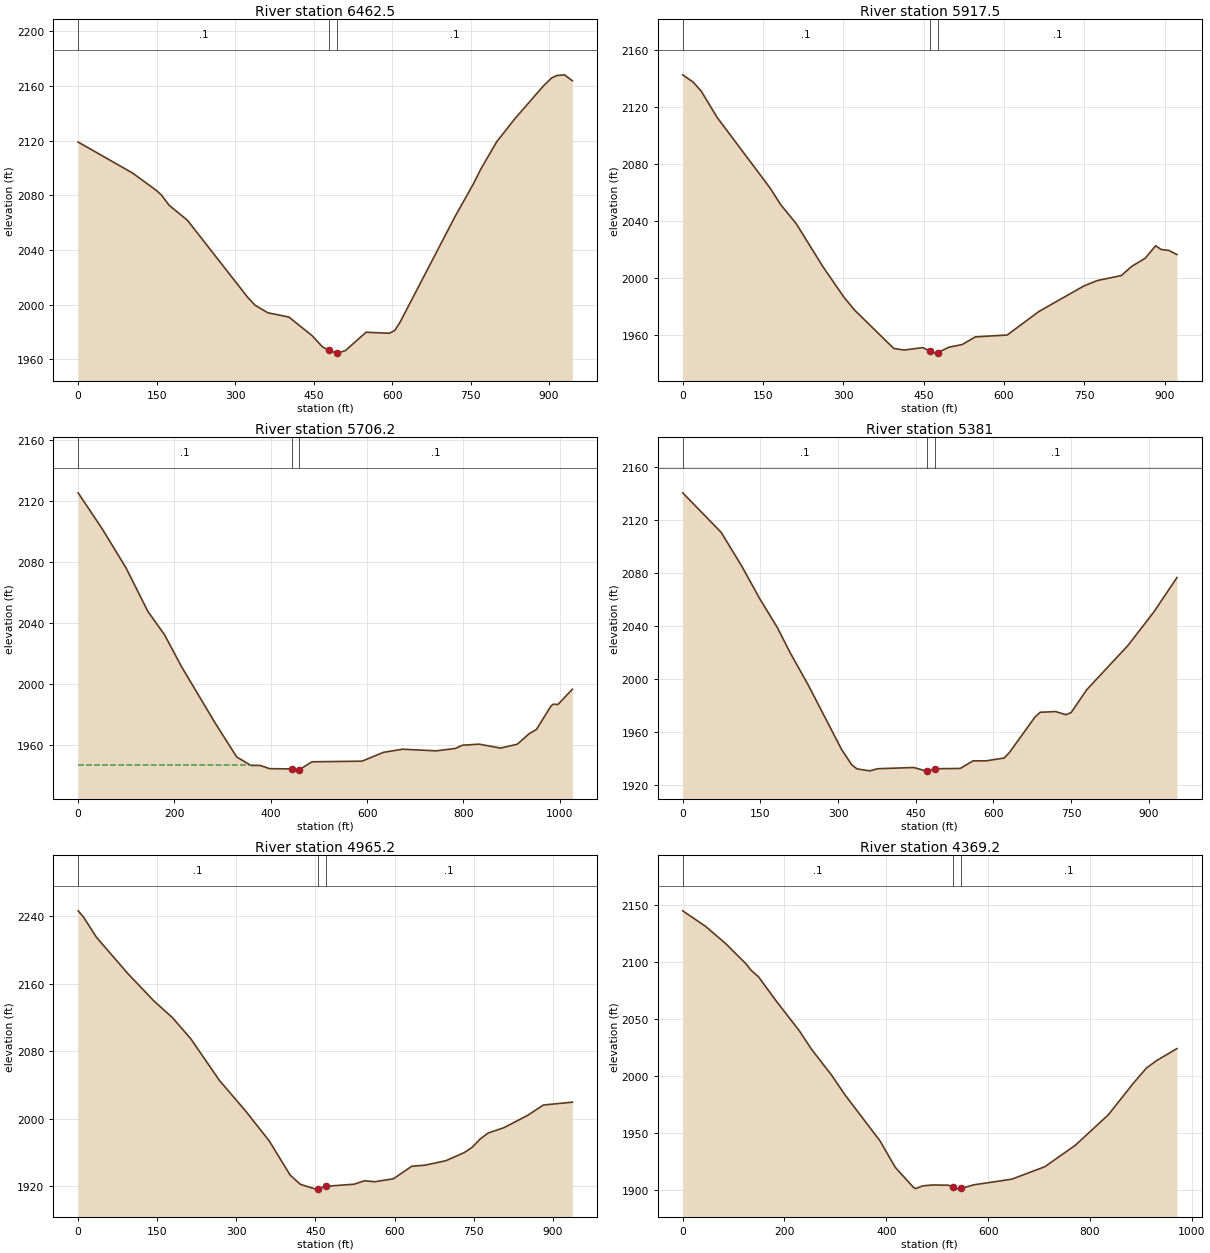
Type RM Length L Ch R = 1 ,6462.5  ,546.9,545,543.2
XS GIS Cut Line= 4
     1827841.706      279506.276     1827994.051      279905.673
     1827984.792      280032.991      1827916.83      280416.289
#Sta/Elev= 30
       0 2118.98   104.4 2096.19   149.1 2083.67   159.1 2080.23     174 2072.65
   208.8 2061.74   323.1 2005.73     338 1999.48   362.8 1993.92   402.6 1990.87
   447.1 1977.22   466.7 1969.06   478.9 1966.47   493.9 1964.43   496.2 1964.41
   510.9 1966.32   550.2  1979.7     595 1978.97     605 1981.06     615 1986.92
   719.8 2064.12   754.8 2087.97   769.7 2099.34   799.7 2119.11   834.6 2136.08
   889.5 2160.24   904.5 2165.84   914.4 2167.67   929.4  2168.2   944.4 2163.88
#Mann= 3 , 0 , 0
       0      .1       0   478.9    .045       0   493.9      .1       0
Bank Sta=478.9,493.9
XS Rating Curve= 0 ,0
Exp/Cntr=0.3,0.1

Type RM Length L Ch R = 1 ,5917.5  ,210.3,211.3,212.1
XS GIS Cut Line= 3
     1827390.062      279554.655     1827452.372      279829.283
     1827609.783      280440.408
#Sta/Elev= 30
       0 2142.85    19.8 2137.66    34.6 2131.35    64.2 2112.92     163  2063.3
   182.8 2051.62   212.4 2037.91   261.8 2007.88   301.2 1986.35   320.8 1977.38
   394.1 1950.36   413.7 1949.22     448 1950.94   460.9 1948.77   472.4 1947.05
   475.9 1947.31   496.9  1951.2   521.7 1953.05   546.4 1958.49   605.9 1959.79
   665.3 1976.38   749.5 1994.38   774.3 1998.12   818.9 2001.62   838.7 2008.14
   863.4 2013.72   883.2  2022.6   893.2 2020.01     908 2019.28   922.9 2016.41
#Mann= 3 , 0 , 0
       0      .1       0   460.9    .045       0   475.9      .1       0
Bank Sta=460.9,475.9
XS Rating Curve= 0 ,0
Exp/Cntr=0.3,0.1

Type RM Length L Ch R = 1 ,5706.2  ,321,325.2,329.5
XS GIS Cut Line= 4
     1827325.055      279535.294     1827255.609      279857.061
     1827244.034       280042.25     1827570.431      280435.778
#Sta/Elev= 30
       0 2125.17    49.9 2101.68    99.8 2075.88   144.6 2047.73   179.6 2032.23
   214.5 2011.57   284.3 1974.71   329.2 1952.44   358.5 1946.92     378 1946.86
   397.5 1944.78     444  1944.6   451.2 1943.16     459 1944.05   485.4 1949.26
   589.2 1949.67   633.9 1955.45   673.6  1957.5   743.1 1956.41   782.8 1957.96
   797.7 1960.09   832.4  1960.8   877.1 1958.22   911.8 1960.77   936.6  1967.7
   951.5 1970.43   981.3 1985.59   986.3 1986.92   996.2 1986.75    1026 1996.72
#Mann= 3 , 0 , 0
       0      .1       0     444    .045       0     459      .1       0
#XS Ineff= 2 , 0
          370.97 1947.09
Permanent Ineff=
       F       F
Bank Sta=444,459
XS Rating Curve= 0 ,0
Exp/Cntr=0.3,0.1

Type RM Length L Ch R = 1 ,5381    ,419,415.7,411.7
XS GIS Cut Line= 4
      1827130.74      279488.882     1826976.992      279799.066
      1826923.75      280012.034     1826948.318       280399.72
#Sta/Elev= 30
       0 2140.42    74.2 2110.64   113.8 2085.28   148.4  2060.8     183  2038.6
   207.7 2019.64   242.3 1995.54   306.6 1946.96   326.4 1935.29   336.3 1932.25
   361.2 1930.72   376.1 1932.34     446 1933.26   470.9 1930.53   471.9 1930.67
   486.9 1932.32   535.8 1932.56   560.7 1938.29   585.6 1938.28   620.5 1940.42
   630.5 1944.44   680.3  1971.4   690.2 1974.92   720.1 1975.44     740 1973.07
     750  1974.7   779.9 1991.86   859.6 2025.29   909.4 2050.44   954.2 2076.51
#Mann= 3 , 0 , 0
       0      .1       0   471.9    .045       0   486.9      .1       0
Bank Sta=471.9,486.9
XS Rating Curve= 0 ,0
Exp/Cntr=0.3,0.1

Type RM Length L Ch R = 1 ,4965.2  ,584.9,596,607.2
XS GIS Cut Line= 4
     1826416.706      279444.532     1826563.463      279808.449
     1826561.148      279958.915     1826585.269      280352.463
#Sta/Elev= 30
       0 2246.43     9.9 2239.32    34.8 2215.06    94.4 2171.96     144 2139.39
   178.8 2119.81   213.6 2094.76   268.2 2045.16   317.9  2008.9   362.6 1973.46
   402.1 1933.09   421.5 1922.14   450.6 1916.47   454.8 1916.92   469.8 1919.82
   523.5 1922.32   542.9 1926.36   562.8 1925.24   597.8 1928.73   632.7  1943.6
   657.7 1944.85   697.6 1950.22   732.5 1959.88   747.5 1966.24   762.5 1975.93
   777.4 1982.94   807.4  1989.3   852.3  2003.9   882.3  2016.2   937.2 2019.56
#Mann= 3 , 0 , 0
       0      .1       0   454.8    .045       0   469.8      .1       0
Bank Sta=454.8,469.8
XS Rating Curve= 0 ,0
Exp/Cntr=0.3,0.1

Type RM Length L Ch R = 1 ,4369.2  ,464.7,458,451.2
XS GIS Cut Line= 4
     1826195.399      279336.216     1826031.044      279773.726
     1825947.708      279926.507     1825901.411      280252.903
#Sta/Elev= 30
       0 2145.27    44.8 2131.65    84.5 2116.43   124.3  2098.7   134.2 2093.07
   149.2 2087.09     184 2065.81   228.7 2040.03   253.6 2023.23   293.3  2000.3
   318.2 1983.82   387.8 1942.85   417.6 1919.69   452.4 1902.52   457.4 1900.92
   472.3 1903.42   492.2 1904.18   522.1 1903.92     532 1902.21     542  1900.5
     547 1901.11   571.8 1904.27   646.4 1909.23   711.3 1920.16   771.3 1939.02
   836.2 1965.84   886.1    1994   911.1 2006.96   931.1 2013.54   971.1 2024.09
#Mann= 3 , 0 , 0
       0      .1       0     532    .045       0     547      .1       0
Bank Sta=532,547
XS Rating Curve= 0 ,0
Exp/Cntr=0.3,0.1

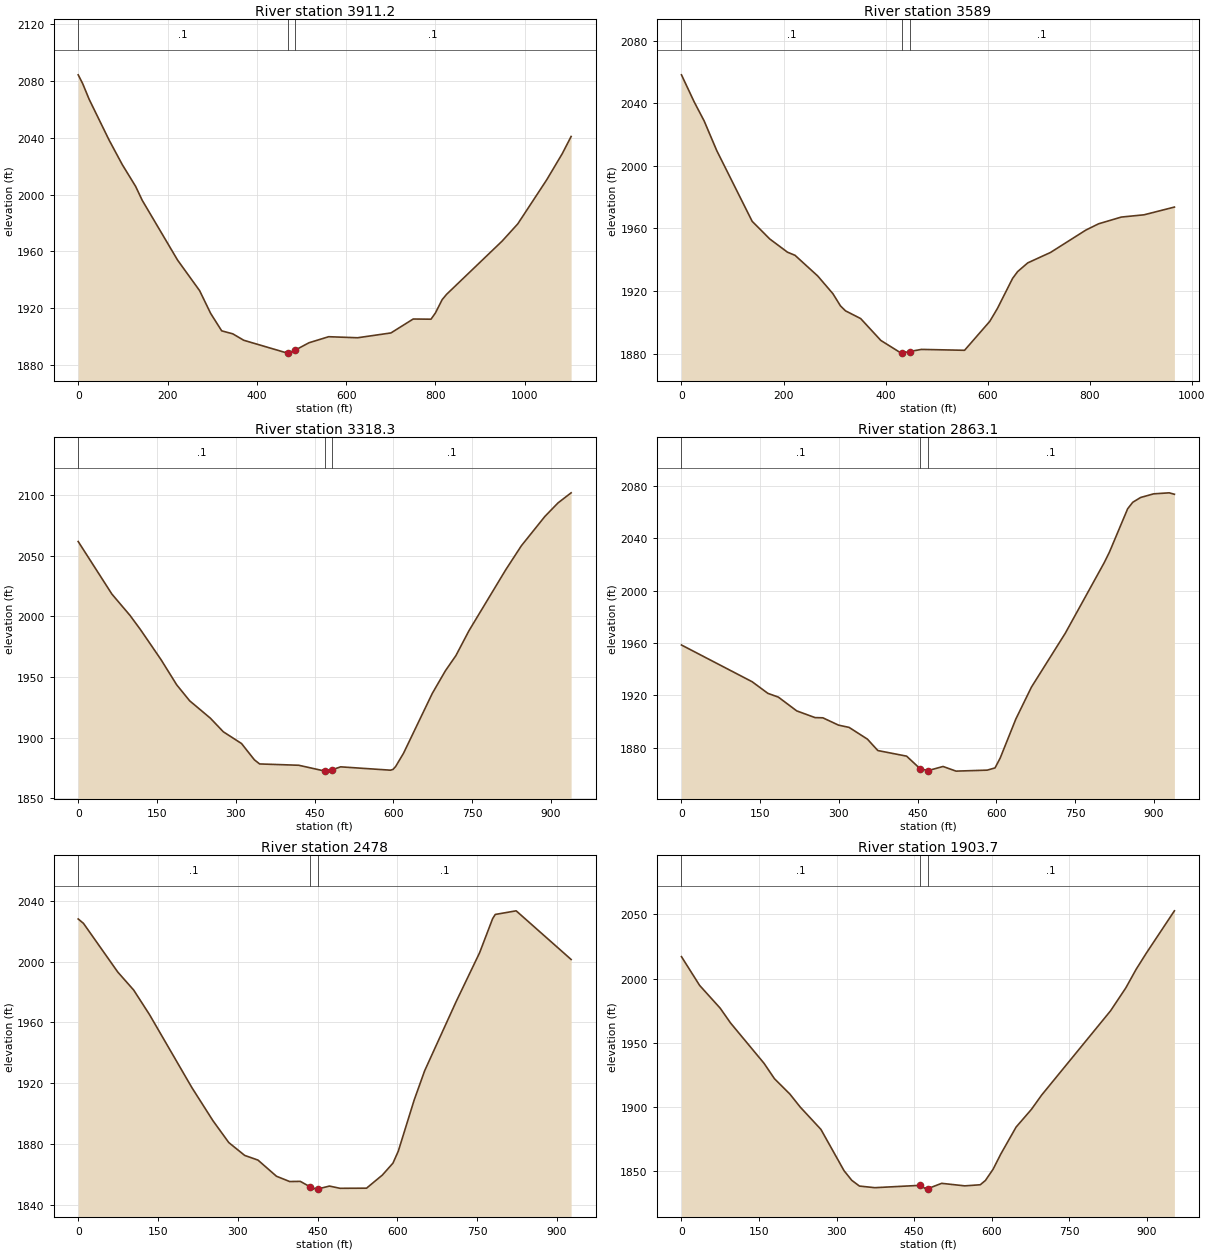
Type RM Length L Ch R = 1 ,3911.2  ,304.5,322.2,339.9
XS GIS Cut Line= 4
     1825958.385      279092.439     1825737.056      279449.644
     1825711.592      279567.703     1825697.703      280130.215
#Sta/Elev= 30
       0 2084.44     9.9 2078.36    24.7 2067.09    69.2 2038.47    98.9 2021.07
   128.5 2005.89   143.4 1996.01   222.5  1953.9   271.9 1932.34   296.6 1916.31
   321.3 1904.03   346.1 1901.92   370.8 1897.37   468.5 1888.32   470.3 1888.41
   485.3 1890.34   516.8 1895.63   560.9 1899.89   625.6 1899.15   700.3 1902.55
   750.1 1912.36     790 1912.23   799.9 1916.66   814.9 1925.98   824.8 1929.73
   949.3  1967.3   984.2 1979.38  1048.9 2010.39  1083.8 2028.85  1103.7 2040.99
#Mann= 3 , 0 , 0
       0      .1       0   470.3    .045       0   485.3      .1       0
Bank Sta=470.3,485.3
XS Rating Curve= 0 ,0
Exp/Cntr=0.3,0.1

Type RM Length L Ch R = 1 ,3589    ,282.4,270.7,258.9
XS GIS Cut Line= 4
     1825746.315       278914.91     1825554.181      279255.195
     1825456.957      279324.641     1825345.843      279766.781
#Sta/Elev= 30
       0 2058.13    24.7 2040.97    44.5 2028.63    69.2 2009.66   138.5 1964.54
   173.1 1953.21   207.8 1944.78   222.6 1942.78   267.1 1929.56   296.8 1918.26
   311.6 1910.48   321.5  1907.3   351.2 1902.36   390.8 1888.37   430.6 1880.27
     432 1880.33     447 1881.28   470.4 1882.65   554.9 1882.08   604.4 1900.62
   619.3 1908.82     649 1928.02   658.9 1932.37   678.7 1937.94   723.3  1944.6
   792.7 1958.92   817.5 1962.91   862.1 1967.22   906.7 1968.67   966.2 1973.61
#Mann= 3 , 0 , 0
       0      .1       0     432    .045       0     447      .1       0
Bank Sta=432,447
XS Rating Curve= 0 ,0
Exp/Cntr=0.3,0.1

Type RM Length L Ch R = 1 ,3318.3  ,445.6,455.2,464.9
XS GIS Cut Line= 3
     1825618.633      278790.147     1825338.898      279039.913
     1825109.409      279554.298
#Sta/Elev= 30
       0 2061.66    64.2 2018.33    98.7 2000.74   118.4 1989.17   157.9 1964.18
   187.5 1943.58   212.2 1930.41   251.6  1916.1   276.3 1904.87   310.9 1895.21
   335.5 1881.74   345.4 1878.39   419.9  1877.3     469 1872.56   469.7 1872.47
     484 1873.68   499.6    1876   594.3 1873.25   599.3 1873.88   604.3  1876.3
   619.3 1887.21   674.1 1936.55     699 1955.16     719 1967.67   743.9  1988.2
   813.6  2038.2   843.6 2058.16   888.4 2082.34   913.4 2093.48   938.3 2101.77
#Mann= 3 , 0 , 0
       0      .1       0     469    .045       0     484      .1       0
Bank Sta=469,484
XS Rating Curve= 0 ,0
Exp/Cntr=0.3,0.1

Type RM Length L Ch R = 1 ,2863.1  ,379.9,385.1,390.4
XS GIS Cut Line= 4
     1825181.011      278602.285     1824917.592      278921.854
     1824750.922      279070.006     1824684.023      279364.678
#Sta/Elev= 30
       0 1958.53   134.7 1930.48   164.7 1921.62   184.6 1918.77   219.6 1908.25
   254.5 1903.13   269.4 1902.96   299.4 1897.35   319.3 1895.67   354.3 1886.69
   374.2 1877.98     429  1873.7   454.5  1864.2   469.5 1862.61   498.4 1865.82
   523.2 1862.27   582.6 1863.02   597.5 1864.73   607.4 1872.31   637.1    1902
   666.9 1926.42   731.3 1967.48   805.6 2021.41   815.5 2029.44   850.2  2062.5
     860 2067.48   874.9 2071.11   899.7 2073.89   929.4 2074.67   939.3 2073.57
#Mann= 3 , 0 , 0
       0      .1       0   454.5    .045       0   469.5      .1       0
Bank Sta=454.5,469.5
XS Rating Curve= 0 ,0
Exp/Cntr=0.3,0.1

Type RM Length L Ch R = 1 ,2478    ,572.2,574.3,576.4
XS GIS Cut Line= 4
     1825058.984      278433.661     1824824.998      278574.624
     1824500.916       278738.98     1824212.251      278767.043
#Sta/Elev= 30
       0 2028.11     9.9 2025.23    74.5 1993.11   104.3  1981.3   134.1  1965.1
   213.6 1917.12   253.3 1895.27   283.1 1880.85     313 1872.39   337.9 1869.33
   372.7 1858.68   397.6 1855.18   417.5  1855.3     436 1851.69   447.4 1850.19
     451 1850.35   472.3  1852.2   492.2 1850.73     542 1850.81   571.8 1859.46
   591.7 1867.31   601.7 1875.18   631.6  1908.9   651.3 1928.16   710.3 1973.56
   754.5 2005.81   779.1 2028.35     784 2031.08   823.3 2033.47   926.6 2001.44
#Mann= 3 , 0 , 0
       0      .1       0     436    .045       0     451      .1       0
Bank Sta=436,451
XS Rating Curve= 0 ,0
Exp/Cntr=0.3,0.1

Type RM Length L Ch R = 1 ,1903.7  ,499.2,497.8,496.4
XS GIS Cut Line= 4
     1824933.481      278124.251     1824674.531      278049.149
     1824348.135      278169.523     1824013.139      278190.802
#Sta/Elev= 30
       0 2017.04      35 1994.74    74.9 1976.96    94.9 1965.46   159.8 1934.03
   179.8 1922.14   209.7 1910.16   229.7 1900.05   269.6 1882.75   314.4 1850.59
   329.3 1843.12   344.2 1838.64     374 1837.39   461.4 1839.21   473.4 1836.27
   476.4 1836.67   503.2 1840.77   547.9 1838.81   577.8 1839.67   587.7 1842.98
   602.6 1851.76   617.5 1863.58   647.1 1884.53   676.7  1898.3   696.5 1909.42
   829.8 1974.97   859.4 1992.87   879.1 2007.15   898.9 2019.79   953.2 2052.68
#Mann= 3 , 0 , 0
       0      .1       0   461.4    .045       0   476.4      .1       0
Bank Sta=461.4,476.4
XS Rating Curve= 0 ,0
Exp/Cntr=0.3,0.1