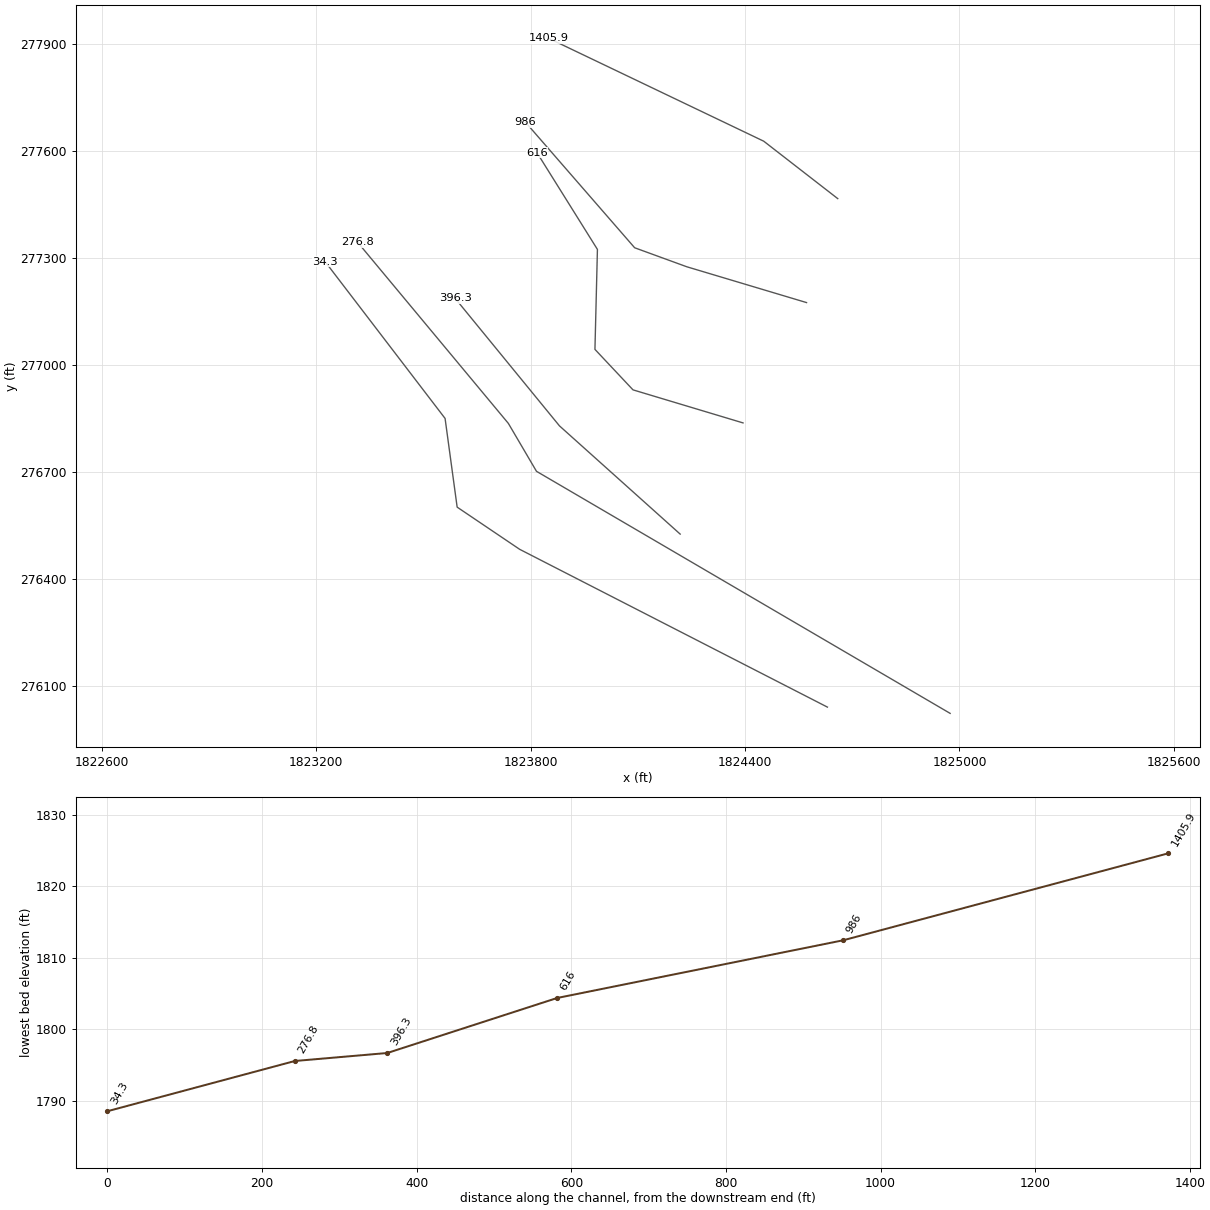
HEC-RAS study ClearFk.prj: ClearFk

--- ClearFk.g01 (geometry) --- (continued)

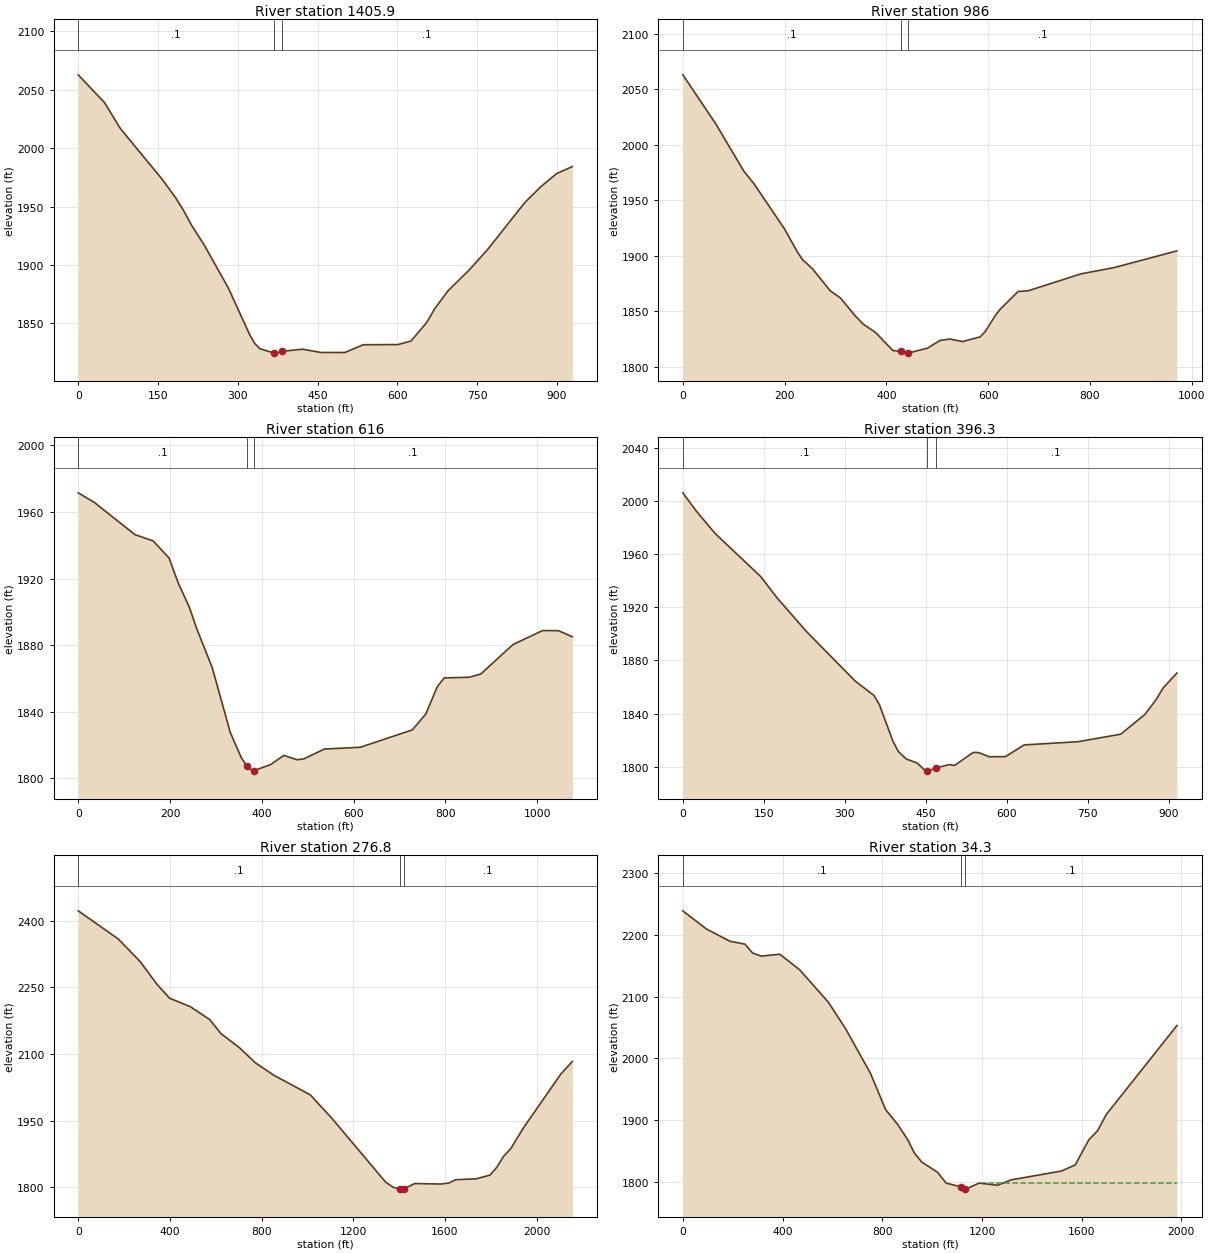
Type RM Length L Ch R = 1 ,1405.9  ,417.7,419.9,422.1
XS GIS Cut Line= 3
     1824659.465      277466.899     1824452.304      277627.843
     1823850.767      277916.034
#Sta/Elev= 30
       0  2062.9    49.5 2039.08    79.2 2016.95   158.4 1973.17   183.1  1957.7
     198 1946.85   212.8 1934.39   237.6 1916.68   282.2  1880.5   322.1 1840.77
     332 1832.86     342 1828.31   367.7 1824.83   371.8 1824.63   382.7 1826.13
   421.6    1828   456.5 1825.19   501.3 1825.14   536.1 1831.84   600.8 1831.92
   625.7 1834.94   655.6    1851   670.5 1862.69   695.4 1877.98   735.2 1895.79
   770.1 1913.42   839.7 1953.46   869.6 1966.98   899.5 1978.27   929.3 1984.37
#Mann= 3 , 0 , 0
       0      .1       0   367.7    .045       0   382.7      .1       0
Bank Sta=367.7,382.7
XS Rating Curve= 0 ,0
Exp/Cntr=0.3,0.1

Type RM Length L Ch R = 1 ,986     ,380.3,370.1,359.9
XS GIS Cut Line= 4
     1824572.141      277175.628     1824237.021      277275.984
     1824091.185      277329.226     1823785.622      277681.085
#Sta/Elev= 30
       0 2063.18      65 2018.85   119.9 1976.42   139.9 1965.01   199.9 1924.33
   224.9 1903.73   234.9 1896.89   254.9  1888.4   289.8  1868.6   309.8 1862.18
   339.8 1845.51   354.7 1838.56   378.9 1831.02   412.9 1814.79   428.5 1814.12
     442 1812.46   443.5 1812.57   480.8 1816.91   505.1  1823.8   524.9 1825.17
   549.7 1822.86   584.4 1827.12   594.3 1831.89   614.1 1846.28   624.1 1852.23
   658.8 1867.95   678.6  1868.6   782.7 1883.91   847.2 1889.46   971.1 1904.57
#Mann= 3 , 0 , 0
       0      .1       0   428.5    .045       0   443.5      .1       0
Bank Sta=428.5,443.5
XS Rating Curve= 0 ,0
Exp/Cntr=0.3,0.1

Type RM Length L Ch R = 1 ,616     ,218.8,219.7,218.1
XS GIS Cut Line= 5
     1824394.432      276838.474     1824086.555      276931.068
     1823980.071      277044.497     1823987.016      277324.596
      1823818.03      277595.435
#Sta/Elev= 30
       0 1971.51    34.6 1965.84   123.6  1946.4   163.2 1942.64   197.8 1932.38
   217.6 1917.53   242.4 1902.58   257.2  1890.6   291.8 1866.62   331.2 1827.63
   355.5 1812.28   367.6 1807.45   379.8 1804.37   382.6 1804.67   418.7 1808.24
   447.9  1813.8   477.1 1811.19   491.8 1811.77   536.1 1817.62   614.7 1818.72
   727.8 1829.12   757.3  1838.7   782.2 1855.06   797.2 1860.34     852 1860.76
     877 1862.69   946.8 1880.32  1011.6  1888.8  1046.6 1888.71  1076.5 1885.05
#Mann= 3 , 0 , 0
       0      .1       0   367.6    .045       0   382.6      .1       0
Bank Sta=367.6,382.6
XS Rating Curve= 0 ,0
Exp/Cntr=0.3,0.1

Type RM Length L Ch R = 1 ,396.3   ,125.5,119.5,116
XS GIS Cut Line= 3
     1824218.512      276526.957     1823880.822      276830.152
     1823588.763      277187.651
#Sta/Elev= 30
       0 2006.04    24.9 1992.37    59.8  1975.5   144.6 1942.93   174.6 1927.02
   229.4 1901.56   319.2  1864.5   354.1 1853.62   364.1 1846.78     389 1819.48
     399  1811.6   413.9  1805.8   433.9 1802.86   448.8 1797.17   453.2 1796.73
   453.8 1796.66   468.2 1798.95   493.5 1801.54   503.5 1800.95   538.2 1810.76
   548.1 1810.63     568 1807.44   597.8 1807.59   632.5  1816.4   731.8 1818.78
   811.2 1824.42   855.9  1839.2   875.8 1849.84   890.6 1859.56   915.5 1870.46
#Mann= 3 , 0 , 0
       0      .1       0   453.2    .045       0   468.2      .1       0
Bank Sta=453.2,468.2
XS Rating Curve= 0 ,0
Exp/Cntr=0.3,0.1

Type RM Length L Ch R = 1 ,276.8   ,232.3,242.5,252.6
XS GIS Cut Line= 4
     1824973.927      276024.609     1823816.494      276702.865
     1823737.788      276837.128     1823316.482      277344.084
#Sta/Elev= 30
       0 2422.09   174.6 2358.76   269.3 2308.41   344.1 2256.32     399  2225.3
   488.7 2206.41   573.5 2177.41   623.4 2145.47   703.2 2114.06     773 2079.94
   852.8 2052.15  1012.4 2007.89  1107.1 1954.87  1341.5 1811.28  1375.6 1799.43
  1405.1 1795.82  1414.5 1795.54  1420.1 1796.06    1468  1808.1    1582 1807.02
    1617 1809.15    1647  1816.7  1736.8 1818.72  1796.8 1827.16  1826.7 1844.75
  1856.7 1869.69  1886.7 1886.08  1941.6 1932.52  2106.4 2054.94  2156.3 2082.94
#Mann= 3 , 0 , 0
       0      .1       0  1405.1    .045       0  1420.1      .1       0
Bank Sta=1405.1,1420.1
XS Rating Curve= 0 ,0
Exp/Cntr=0.3,0.1

Type RM Length L Ch R = 1 ,34.3    ,30,34.3,38.6
XS GIS Cut Line= 5
     1824630.549      276042.159     1823769.418      276484.299
     1823594.511      276602.473     1823560.742      276851.011
     1823225.424      277289.873
#Sta/Elev= 30
       0 2238.72    94.8 2209.32   189.6  2189.4   249.5 2184.85   279.4 2170.61
   314.4 2165.49   389.2 2168.49     469 2143.28   583.8 2090.92   653.6 2047.56
   753.4 1975.27   813.3 1917.34   863.2 1892.44   903.1  1867.8   928.1 1847.38
     958 1832.52    1022 1815.74  1056.4 1798.25  1117.8 1791.96  1132.8 1788.81
  1134.9  1788.5  1188.9 1798.29  1262.7 1794.77  1316.8 1803.46  1519.5 1817.82
  1574.2 1827.73  1628.9 1868.46  1663.8  1882.9  1698.6 1909.18  1982.2 2053.15
#Mann= 3 , 0 , 0
       0      .1       0  1117.8    .045       0  1132.8      .1       0
#XS Ineff= 2 , 0
                         1191.51         1798.33
Permanent Ineff=
       F       F
Bank Sta=1117.8,1132.8
XS Rating Curve= 0 ,0
Exp/Cntr=0.3,0.1

Chan Stop Cuts=-1
Use User Specified Reach Order=0